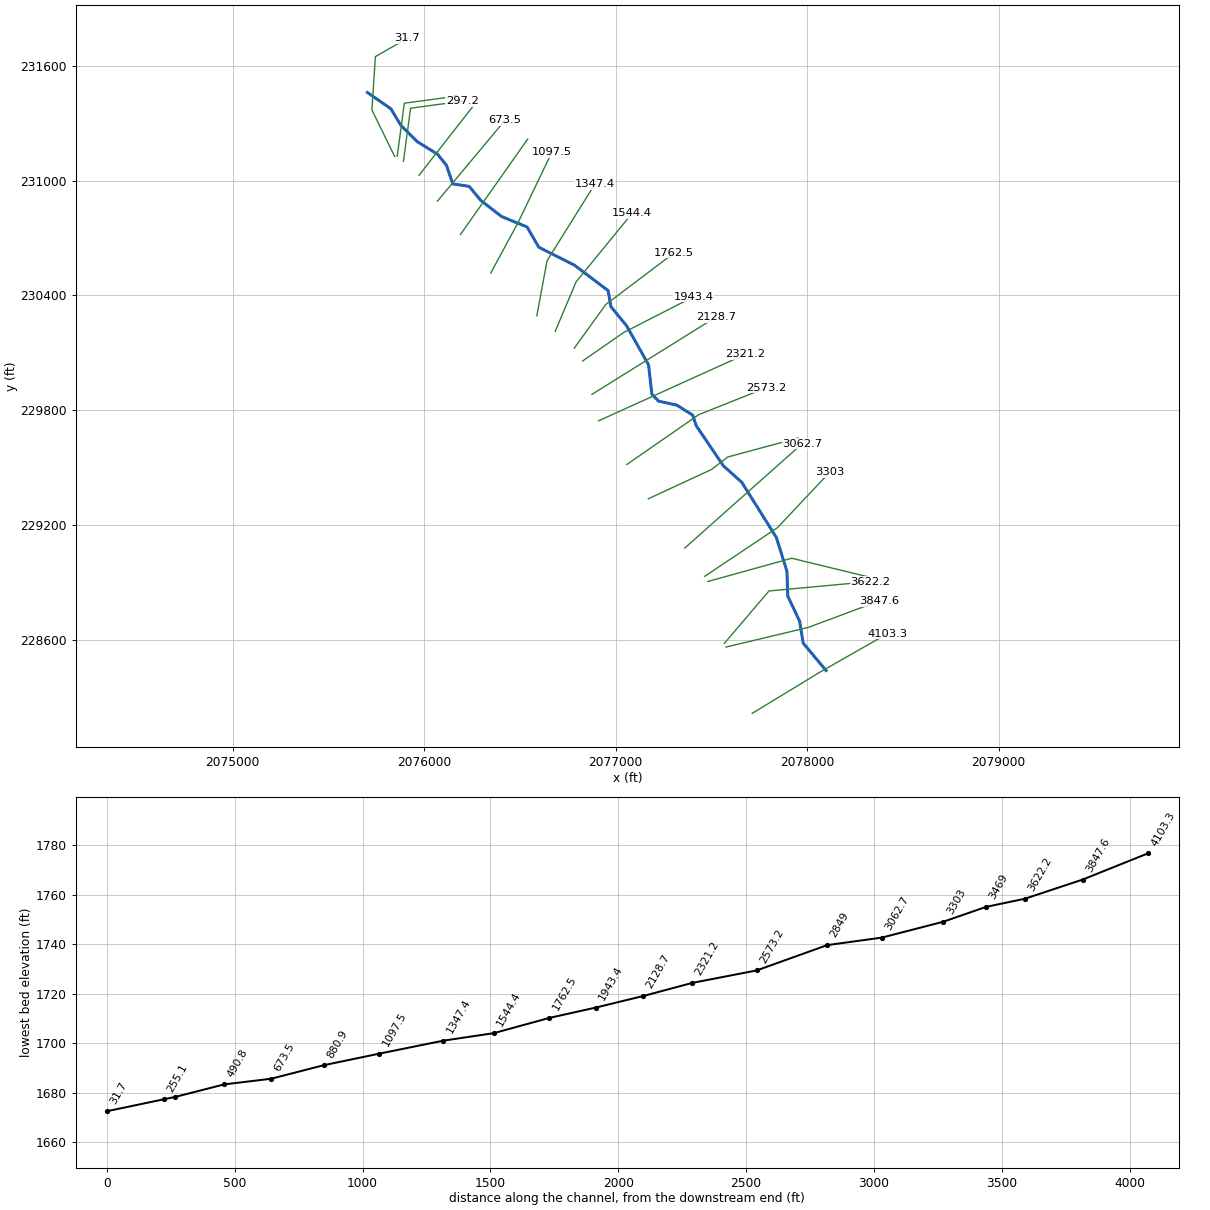
--- WOLFCKT1.prj (project) ---

Proj Title=WOLFCKT1
Current Plan=p01
Default Exp/Contr=0,0
English Units
Geom File=g01
Flow File=f01
Plan File=p01
BEGIN DESCRIPTION:
END DESCRIPTION:
DSS Export Rating Curves= 0
DSS Export Rating Curve Sorted= 0
DSS Export Volume Flow Curves= 0
DXF OffsetX= 0
DXF OffsetY= 0
DXF ScaleX= 0
DXF ScaleY= 0

--- WOLFCKT1.p01 (plan) ---

Plan Title=Floodplain
Program Version=4.00
Geom File=g01
Flow File=f01
K Sum by GR=0
Std Step Tol=0.01
Critical Tol=0.01
Num of Std Step Trials=20
Max Error Tol=0.3
Flow Tol Ratio=0.001
Split Flow NTrial=30
Split Flow Tol=0.02
Split Flow Ratio=0.02
Log Output Level=0
Friction Slope Method=1
Unsteady Friction Slope Method=2
Unsteady Bridges Friction Slope Method=1
Global Log Level=0
CheckData=False
Run HTab=0
Run UNet=0
Run PostProcess=0
UNET Theta=0
UNET Theta Warmup=0
UNET ZTol=0
UNET ZSATol=0
UNET MxIter=0
UNET MaxInSteps=0
UNET DtIC=0
UNET DtMin=0
UNET MaxCRTS=0
UNET WFStab=0
UNET SFStab=0
UNET WFX=0
UNET SFX=0
UNET DSS MLevel=0
UNET DZMax Abort=0
UNET Convert EG Bridges=0
UNET Use Existing IB Tables=0
UNET Froude Limit=0
UNET Froude Power=0
Write IC File=0
Echo Input=False
Echo Output=False
Write Detailed=0

--- WOLFCKT1.f01 (steady flow) ---

Flow Title=NFF Regression Equation
Program Version=4.10
Number of Profiles= 1
Profile Names=P100yr
River Rch & RM=WOLFCKT1,Main            ,4103.3
503.2841
River Rch & RM=WOLFCKT1,Main            ,3847.6
505.4492
River Rch & RM=WOLFCKT1,Main            ,3469
592.0901
River Rch & RM=WOLFCKT1,Main            ,490.8
622.1695
River Rch & RM=WOLFCKT1,Main            ,297.2
623.4443
Boundary for River Rch & Prof#=WOLFCKT1,Main            , 1
Up Type= 0
Dn Type= 3
Dn Slope=0.018
DSS Import GetInterval= 0
DSS Import GetPeak= 0
DSS Import FillOption= 0

--- WOLFCKT1.g01 (geometry) ---

Geom Title=USGS 1m DEM
Program Version=4.10

River Reach=WOLFCKT1        ,Main
Reach XY= 30
     2078098.631      228441.733     2077979.146      228585.121
       2077960.7      228699.053     2077898.851      228830.347
     2077894.511       228959.47     2077839.172      229136.336
     2077659.051       229423.88      2077562.48      229510.685
     2077421.421      229719.019     2077401.889      229775.442
     2077319.424      229827.526     2077223.938      229848.142
     2077189.216      229885.034     2077171.854      230038.029
     2077057.271      230241.588      2076975.24      230341.849
     2076960.917      230425.182     2076785.136      230557.994
     2076598.938      230651.744      2076537.74      230757.213
     2076404.927      230811.901     2076295.552      230896.536
     2076235.657      230969.453     2076149.719      230982.473
     2076117.167      231078.828     2076070.292      231137.422
     2075964.823      231202.526     2075877.584      231289.765
     2075826.803      231374.401     2075704.056      231459.669

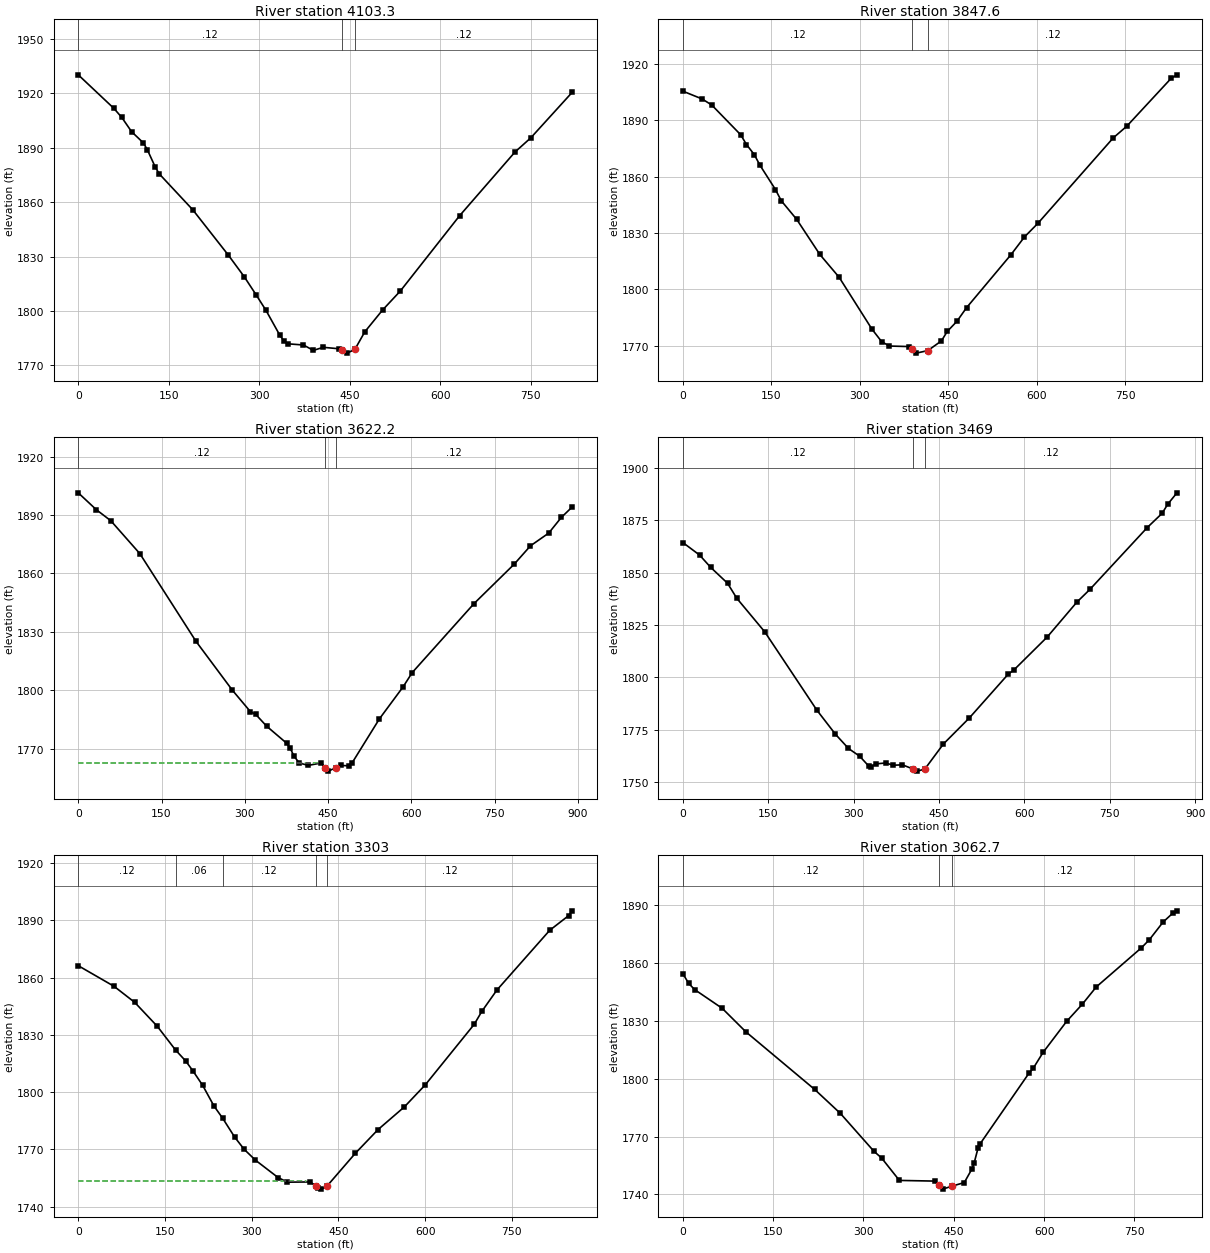
Type RM Length L Ch R = 1 ,4103.3  ,265,255.6,246
XS GIS Cut Line= 3
     2077713.158      228218.004     2078062.923      228430.903
     2078418.813      228633.875
#Sta/Elev= 30
       0 1930.29      59 1911.81    72.1 1906.83    88.4 1898.95   108.1  1892.7
   114.6 1888.94   127.8 1879.34   134.3 1875.66     190  1855.8     249 1830.78
   275.2 1818.93   294.8 1808.99   311.2 1800.41   334.1 1786.72   340.7 1783.67
   347.2 1781.94   373.4 1781.27   389.8  1778.3   406.2    1780   432.4 1779.19
   436.6 1778.48   445.5 1776.79   458.6 1778.82     475  1788.5   504.5 1800.55
     534 1811.05   632.3  1852.6   724.1 1887.72   750.3 1895.54   819.2 1920.75
#Mann= 3 ,-1 , 0
       0     .12       0   436.6    .045       0   458.6     .12       0
Bank Sta=436.6,458.6
XS Rating Curve= 0 ,0
Exp/Cntr=0.3,0.1

Type RM Length L Ch R = 1 ,3847.6  ,230.2,225.5,219.2
XS GIS Cut Line= 3
     2077576.115      228564.238      2078005.61      228666.731
     2078376.536      228805.015
#Sta/Elev= 30
       0 1905.38    32.7 1901.24    49.1    1898    98.1 1882.19   107.9 1877.02
     121 1871.71   130.8 1865.98     157  1853.1   166.8 1847.16     193 1837.25
   232.2 1818.61   264.9 1806.49   320.5 1778.94   336.9 1772.31     350 1769.96
   382.7 1769.68   389.2 1768.23   395.8 1766.19   415.4 1767.56   438.3 1772.71
   448.1  1777.7   464.5 1783.09   480.8 1790.32   556.1 1818.49     579 1827.92
   601.9  1835.2   729.5 1880.57   752.4 1886.76   827.6  1912.2   837.4 1914.06
#Mann= 3 ,-1 , 0
       0     .12       0   389.2    .045       0   415.4     .12       0
Bank Sta=389.2,415.4
XS Rating Curve= 0 ,0
Exp/Cntr=0.3,0.1

Type RM Length L Ch R = 1 ,3622.2  ,146.4,153.2,159.9
XS GIS Cut Line= 3
     2077567.981      228583.761     2077800.624      228857.075
     2078329.357      228905.881
#Sta/Elev= 30
       0 1901.35    32.6 1892.68    58.7 1887.01   110.9 1870.14   212.1 1825.08
   277.4 1800.07     310 1789.02   319.8 1787.54   339.3 1781.53   375.3  1772.8
   381.9 1770.17   388.4  1766.2   398.2  1762.6   414.6 1761.42   437.6 1762.64
   445.3 1760.21   450.7 1758.46   463.8 1760.25   473.6 1761.38   486.8 1761.19
   493.3 1762.73   542.5 1785.34   585.1 1801.74   601.5 1809.06   712.9 1844.51
     785 1864.67   814.5 1874.15   847.3 1880.67   870.2 1888.77   889.9 1894.17
#Mann= 3 ,-1 , 0
       0     .12       0   445.3    .045       0   463.8     .12       0
#XS Ineff= 2 , 0
          434.42 1762.64
Permanent Ineff=
       F       F
Bank Sta=445.3,463.8
XS Rating Curve= 0 ,0
Exp/Cntr=0.3,0.1

Type RM Length L Ch R = 1 ,3469    ,153.6,166,178.5
XS GIS Cut Line= 3
      2077481.39       228906.49     2077919.385      229027.897
     2078321.223      228930.284
#Sta/Elev= 30
       0 1864.36    29.4 1858.38      49 1852.47    78.5 1844.92    94.8 1837.72
   143.9 1821.68   235.4 1784.28   268.1 1772.75     291 1765.95   310.6 1762.25
     327 1757.42   330.3  1757.2   340.1 1758.61   356.4 1759.01   369.5 1757.94
   385.8 1758.13   404.2 1756.16     412 1755.12   425.1  1756.1   457.8  1768.1
   503.4 1780.56   571.7 1801.48   581.5 1803.44   640.1 1819.21   692.2 1835.87
     715 1841.93   815.9 1871.53     842 1878.32   851.8 1882.66     868 1888.11
#Mann= 3 ,-1 , 0
       0     .12       0   404.2    .045       0   425.1     .12       0
#XS Ineff= 2 , 0
          356.44 1758.97
Permanent Ineff=
       F       F
Bank Sta=404.2,425.1
XS Rating Curve= 0 ,0
Exp/Cntr=0.3,0.1

Type RM Length L Ch R = 1 ,3303    ,234.8,240.4,244.8
XS GIS Cut Line= 3
     2077465.074      228933.386     2077844.549       229187.33
     2078117.864      229476.913
#Sta/Elev= 30
       0  1866.3      62 1855.47    97.8 1847.04     137 1834.43  168.421822.048
   185.9 1816.33     199 1810.87   215.3 1803.53   234.8 1792.73  249.831786.319
   270.7 1776.38     287 1770.03   306.6 1764.32   345.7 1755.22     362  1752.8
   401.2 1752.92     411 1750.79   414.2  1749.6   420.7 1749.15   430.5  1750.8
   479.4 1767.96   518.6 1780.36   564.3  1792.3   600.2 1803.77   685.1 1835.59
   698.1  1842.3   724.2 1853.51   815.6 1884.84   848.3 1892.53   854.8 1895.06
#Mann= 5 ,-1 , 0
       0     .12       0  168.42     .06       0  249.83     .12       0
     411    .045       0   430.5     .12       0
#XS Ineff= 2 , 0
          394.47 1753.32
Permanent Ineff=
       F       F
Bank Sta=411,430.5
XS Rating Curve= 0 ,0
Exp/Cntr=0.3,0.1

Type RM Length L Ch R = 1 ,3062.7  ,216.1,213.6,210.5
XS GIS Cut Line= 2
     2077361.368      229081.583     2077974.699      229626.586
#Sta/Elev= 30
       0 1854.61     9.8 1849.51    19.6 1846.34    65.4  1836.6   104.6 1824.42
     219 1794.47   261.5 1782.08   317.1 1762.46   330.2 1758.84   359.6 1747.25
   418.4  1746.9     425 1744.63   431.5 1742.73   447.8 1744.35   467.4 1746.14
   480.5 1753.43   483.8 1756.37   490.3 1764.14   493.6 1766.22   575.3 1803.15
   581.9 1805.49   598.2 1813.71   637.4 1829.86   663.6 1838.82   686.5 1847.69
   761.6 1868.05   774.7 1872.22   797.6 1881.42     814 1886.12   820.5 1887.22
#Mann= 3 ,-1 , 0
       0     .12       0     425    .045       0   447.8     .12       0
Bank Sta=425,447.8
XS Rating Curve= 0 ,0
Exp/Cntr=0.3,0.1

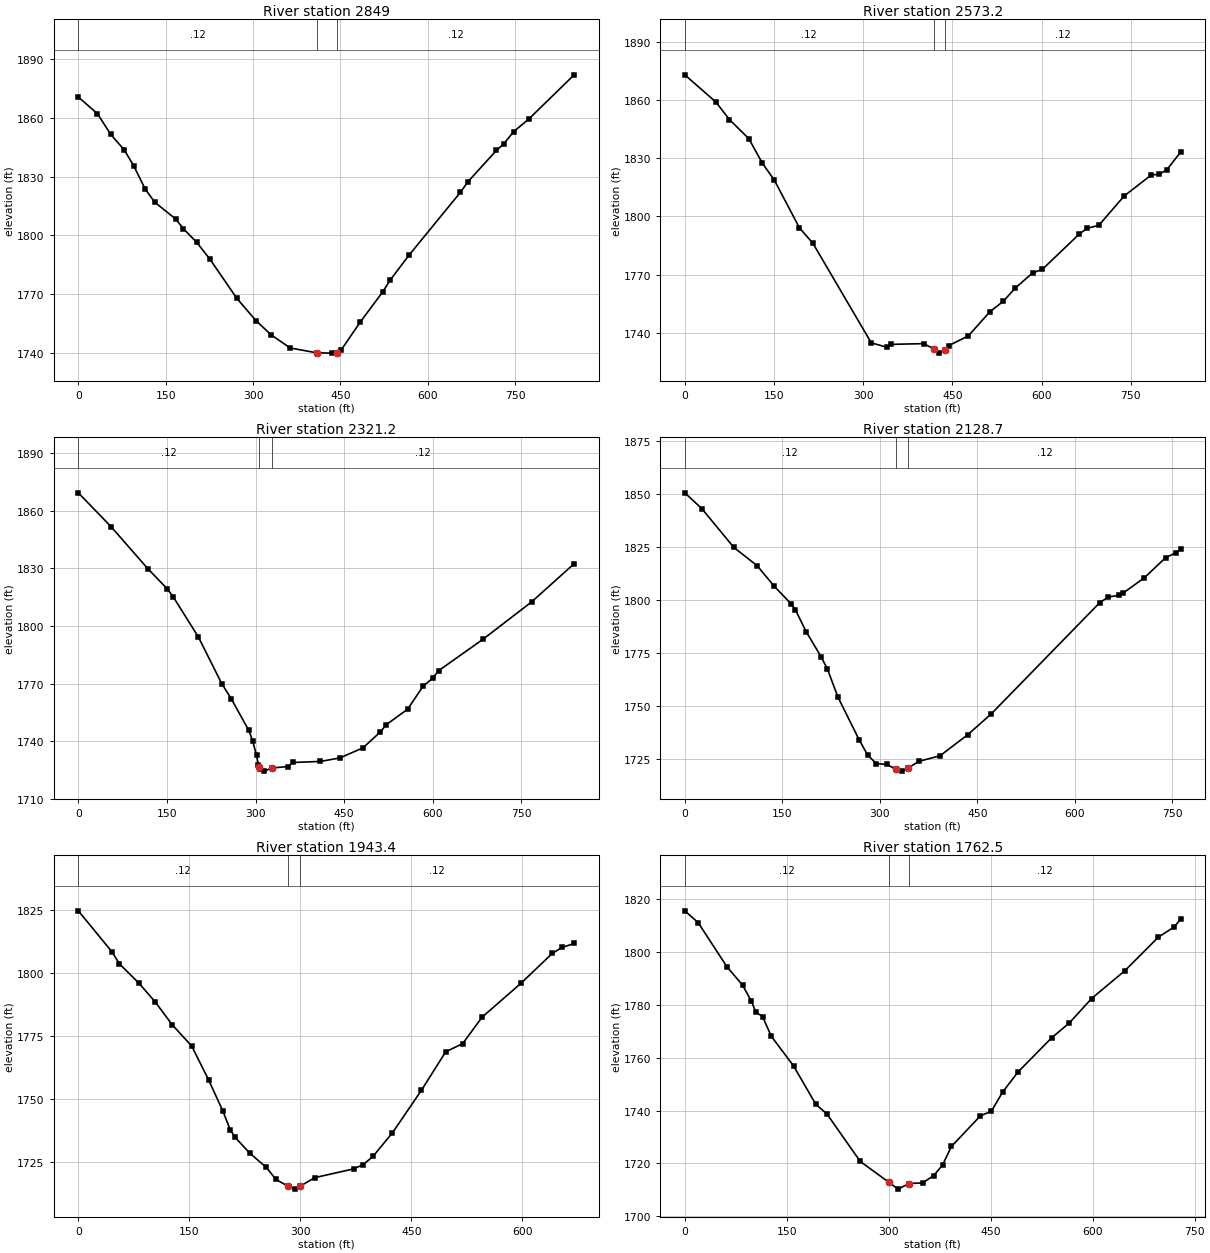
Type RM Length L Ch R = 1 ,2849    ,276,275.8,271.1
XS GIS Cut Line= 4
     2077171.024      229338.629     2077501.279      229491.555
     2077585.877       229556.63      2077953.55      229655.869
#Sta/Elev= 30
       0 1870.74    32.8 1862.22    55.7 1851.59    78.7 1843.73    95.1 1835.56
   114.8 1823.67   131.2 1816.92   167.2 1808.33   180.3 1803.38   203.3  1796.4
   226.2 1787.68   272.1 1767.78   304.9 1756.36   331.2 1749.04   363.9 1742.33
   409.2 1739.87     435  1739.7   444.8  1739.8   451.3 1741.27   483.7 1755.42
   522.8 1771.05   535.8  1777.2   568.3 1789.97   656.2 1821.99   669.2 1827.44
     718 1843.41   731.1 1846.93   747.4 1852.98   773.4 1859.42   851.5  1882.1
#Mann= 3 ,-1 , 0
       0     .12       0   409.2    .045       0   444.8     .12       0
Bank Sta=409.2,444.8
XS Rating Curve= 0 ,0
Exp/Cntr=0.3,0.1

Type RM Length L Ch R = 1 ,2573.2  ,258.7,252,246.2
XS GIS Cut Line= 3
      2077058.77      229517.585     2077434.578      229777.885
     2077784.295       229917.18
#Sta/Elev= 30
       0 1873.14    52.2 1859.11    75.1 1850.03   107.8 1840.12   130.6 1827.41
   150.2 1818.96   192.7 1794.17   215.5  1786.1   313.5 1734.78   339.6 1732.51
   346.1 1733.98   401.6 1734.36   418.3 1731.71   427.8 1729.46   437.6 1730.94
   444.1 1733.39   476.8 1738.39   512.8 1750.79   535.7 1756.28   555.4 1763.01
   584.8 1770.87   601.2 1772.74   663.4 1790.99   676.5 1793.92   696.1 1795.46
   738.7 1810.58   784.5 1821.51   797.6 1821.74   810.7 1824.25   833.6 1833.24
#Mann= 3 ,-1 , 0
       0     .12       0   418.3    .045       0   437.6     .12       0
Bank Sta=418.3,437.6
XS Rating Curve= 0 ,0
Exp/Cntr=0.3,0.1

Type RM Length L Ch R = 1 ,2321.2  ,187.9,192.5,197.1
XS GIS Cut Line= 2
     2076910.725      229745.347     2077675.355      230091.871
#Sta/Elev= 30
       0 1869.36    55.8  1851.6     118 1829.73   150.8 1819.28   160.7 1815.15
   203.3 1794.25   242.7 1770.05   259.1 1762.02   288.6 1745.63   295.1 1740.22
   301.7 1732.61     305 1727.44   306.2 1726.66   308.2 1725.37   314.8 1724.41
   327.9 1726.04   354.2 1726.79     364 1728.92   409.9 1729.47   442.7 1731.26
     482 1736.55   511.6 1744.87   521.4 1748.61   557.5 1756.65   583.7 1768.63
   600.1 1772.86   609.9  1776.7   685.4 1793.15   767.3 1812.51   839.5 1832.44
#Mann= 3 ,-1 , 0
       0     .12       0   306.2    .045       0   327.9     .12       0
Bank Sta=306.2,327.9
XS Rating Curve= 0 ,0
Exp/Cntr=0.3,0.1

Type RM Length L Ch R = 1 ,2128.7  ,187.5,185.3,182.1
XS GIS Cut Line= 2
      2076876.56      229883.631     2077524.055      230287.096
#Sta/Elev= 30
       0 1850.44    26.2 1842.98    75.3 1824.72   111.3 1816.04   137.5  1806.4
   163.7 1798.01   170.3 1795.17   186.6 1784.98   209.6 1773.12   219.4 1767.32
   235.8 1753.89   268.5 1733.74   281.6 1726.55   294.7 1722.68   311.1 1722.22
   324.2 1720.06     334 1719.09   343.8 1720.58   360.2  1723.7   392.9 1726.37
   435.5 1736.32   471.5  1746.1   638.5 1798.62   651.6 1801.29     668 1802.07
   674.5 1803.14   707.2 1810.38     740 1819.89   756.4 1822.22   762.9 1823.92
#Mann= 3 ,-1 , 0
       0     .12       0   324.2    .045       0   343.8     .12       0
Bank Sta=324.2,343.8
XS Rating Curve= 0 ,0
Exp/Cntr=0.3,0.1

Type RM Length L Ch R = 1 ,1943.4  ,168.7,180.9,192.4
XS GIS Cut Line= 3
     2076827.754      230057.707     2077041.759      230206.398
     2077406.352      230392.744
#Sta/Elev= 30
       0 1824.56    45.6 1808.28    55.4 1803.62    81.4 1796.09   104.2  1788.4
     127 1779.42   153.1 1771.08   175.9 1757.74   195.4 1745.29   205.2 1737.93
   211.7 1734.98   231.3 1728.76   254.1    1723   267.1 1718.25   283.5 1715.54
   293.4 1714.43   299.9 1715.64   319.6 1718.98     372 1722.44   385.1 1724.16
   398.2  1727.4   424.4  1736.7   463.7 1753.58   496.4 1768.76   519.4 1772.02
   545.6 1782.48     598 1795.86   640.6 1807.75   653.7 1810.06     670 1811.65
#Mann= 3 ,-1 , 0
       0     .12       0   283.5    .045       0   299.9     .12       0
Bank Sta=283.5,299.9
XS Rating Curve= 0 ,0
Exp/Cntr=0.3,0.1

Type RM Length L Ch R = 1 ,1762.5  ,214.5,218.1,222.4
XS GIS Cut Line= 3
     2076784.156       230124.73     2076948.471      230352.492
     2077306.382      230622.553
#Sta/Elev= 30
       0 1815.59    19.6 1811.14      62 1794.41    84.9 1787.48      98 1781.36
   104.5 1777.22   114.3 1775.58   127.4 1768.05     160 1756.88   192.7 1742.35
     209 1738.72     258 1720.75   300.5 1712.78   313.6 1710.26   329.9 1712.39
   349.6 1712.62   365.9 1715.34     379 1719.35   392.1 1726.41   434.7 1737.98
     451 1739.77   467.4 1746.99   490.3 1754.66   539.4  1767.5   565.6 1773.17
   598.3  1782.4   647.4 1792.97   696.5 1805.64   719.4 1809.42   729.2 1812.39
#Mann= 3 ,-1 , 0
       0     .12       0   300.5    .045       0   329.9     .12       0
Bank Sta=300.5,329.9
XS Rating Curve= 0 ,0
Exp/Cntr=0.3,0.1

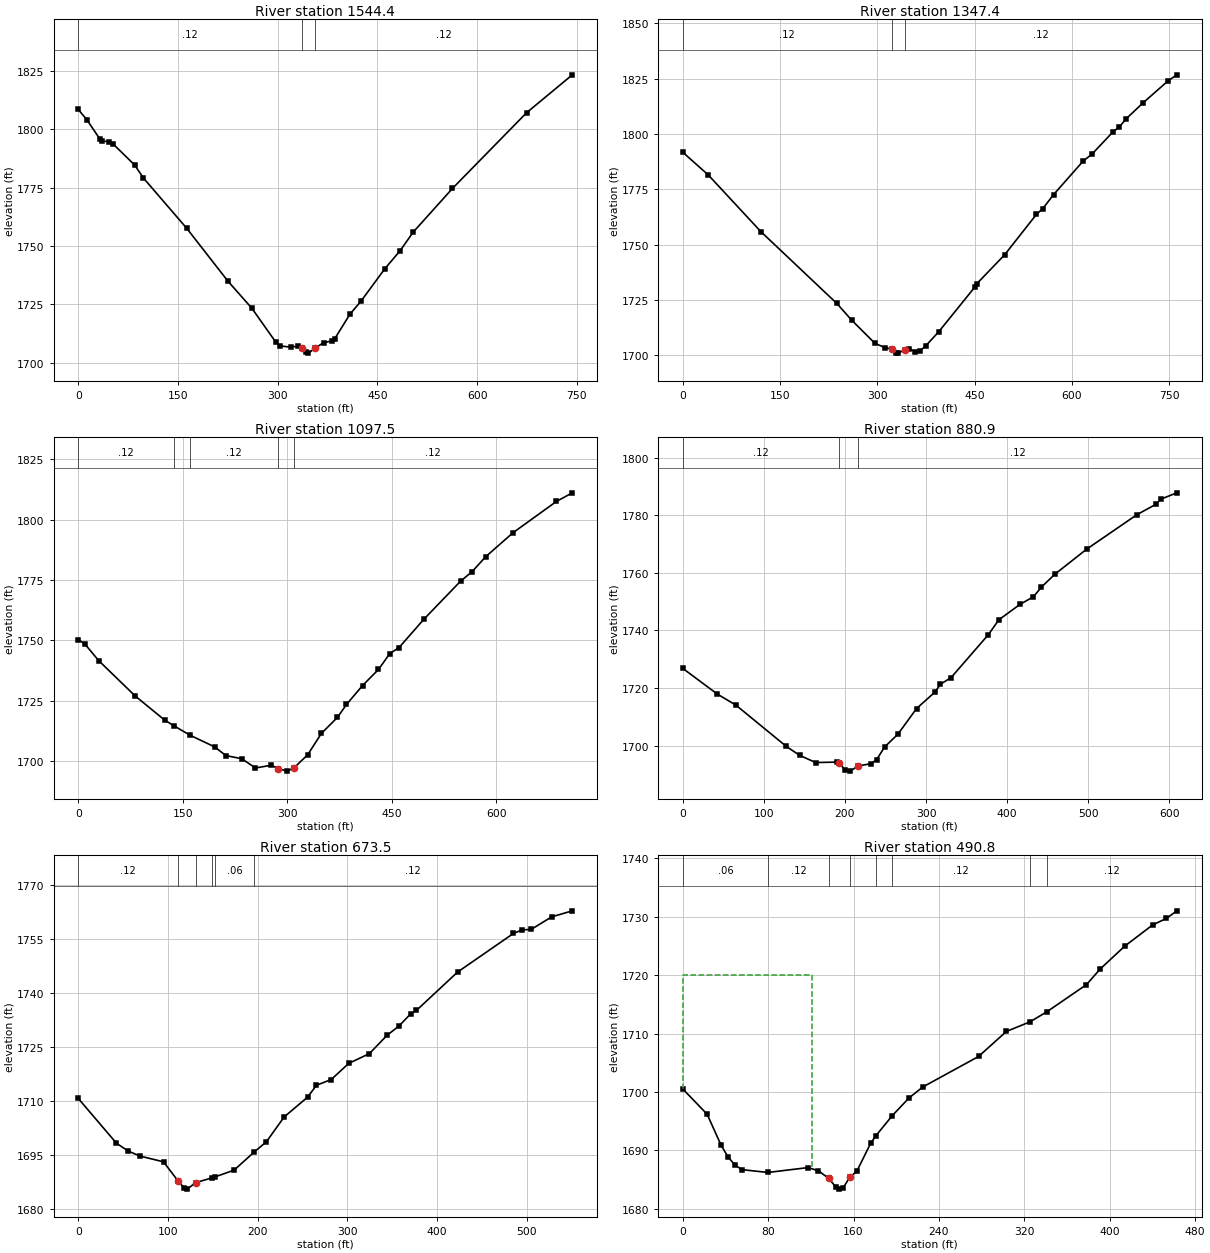
Type RM Length L Ch R = 1 ,1544.4  ,191.9,197,201.6
XS GIS Cut Line= 3
      2076684.59      230212.259      2076793.59      230470.932
     2077086.427      230828.844
#Sta/Elev= 30
       0 1808.44    13.1 1803.99    32.6 1795.76    35.9 1794.96    45.7 1794.62
    52.2 1793.73    84.9 1784.62    97.9 1779.13   163.2 1757.53   225.2 1734.88
   261.1 1723.31   297.1 1708.79   303.7 1707.17   320.1 1706.62   329.9 1707.09
   336.5 1706.35     343 1704.44   346.3 1704.08   356.1  1706.2   369.2 1708.59
   382.4 1709.34   385.6 1710.16   408.6 1720.74     425 1726.23   461.1 1740.22
     484  1747.9   503.7 1755.88   562.8  1774.6   674.3 1807.04   743.1 1823.28
#Mann= 3 ,-1 , 0
       0     .12       0   336.5    .045       0   356.1     .12       0
Bank Sta=336.5,356.1
XS Rating Curve= 0 ,0
Exp/Cntr=0.3,0.1

Type RM Length L Ch R = 1 ,1347.4  ,247.5,249.9,253.7
XS GIS Cut Line= 3
     2076588.604      230293.603     2076642.291      230581.559
     2076890.738      230979.493
#Sta/Elev= 30
       0 1791.71    39.1 1781.54   120.4 1755.91   237.6 1723.47   260.4 1715.96
   296.2 1705.52   312.6 1703.42   322.4    1703     329 1701.17   332.3 1701.05
   342.1 1702.56   348.7 1702.95   358.5 1701.78   365.1 1701.88   374.9 1704.39
   394.6 1710.64   450.4 1730.85   453.7 1732.45   496.3  1745.4   545.5  1763.7
   555.4 1766.33   571.8 1772.58   617.7  1787.8   630.8 1790.78   663.6 1800.94
   673.5  1803.2   683.3 1806.68   709.6 1813.95   748.9 1824.05     762 1826.67
#Mann= 3 ,-1 , 0
       0     .12       0   322.4    .045       0   342.1     .12       0
Bank Sta=322.4,342.1
XS Rating Curve= 0 ,0
Exp/Cntr=0.3,0.1

Type RM Length L Ch R = 1 ,1097.5  ,220.8,216.6,210
XS GIS Cut Line= 3
     2076347.827      230516.485     2076490.718      230780.201
     2076667.743      231149.071
#Sta/Elev= 30
       0 1750.33     9.8  1748.4    29.3 1741.63    81.5 1727.02   123.9 1716.99
  137.351714.594   160.61710.677   195.6 1705.88   211.9 1702.26   234.7 1700.95
   254.3 1697.12   277.1 1698.25   286.9 1696.84   299.9 1695.81   309.8 1697.19
   329.4 1702.63     349 1711.45     372 1718.08     385 1723.43     408 1731.28
   430.9 1737.94   447.2 1744.56   460.3 1746.99   496.3 1758.84   548.7 1774.54
   565.1 1778.44   584.7 1784.67     624 1794.63   686.2 1807.58   709.1 1811.17
#Mann= 5 ,-1 , 0
       0     .12       0  137.35     .06       0   160.6     .12       0
   286.9    .045       0   309.8     .12       0
Bank Sta=286.9,309.8
XS Rating Curve= 0 ,0
Exp/Cntr=0.3,0.1

Type RM Length L Ch R = 1 ,880.9   ,210.5,207.4,203.7
XS GIS Cut Line= 2
      2076190.02      230718.217     2076540.852      231216.293
#Sta/Elev= 30
       0 1726.82    42.6  1717.9    65.5 1714.07   127.7 1699.72   144.1 1696.64
   163.8 1694.13     190 1694.29   193.2 1693.84   199.8 1691.69   206.4 1691.15
   216.2 1692.94   232.6 1693.76   239.1 1695.18   248.9 1699.54   265.3 1703.99
   288.2 1712.86   311.2 1718.67   317.7 1721.32   330.8 1723.61   376.7  1738.5
   389.8  1743.7     416 1749.08   432.4 1751.69   442.2 1755.02   458.6 1759.47
   497.9 1768.19   560.1 1780.21     583 1783.72   589.6 1785.59   609.2 1787.77
#Mann= 3 ,-1 , 0
       0     .12       0   193.2    .045       0   216.2     .12       0
Bank Sta=193.2,216.2
XS Rating Curve= 0 ,0
Exp/Cntr=0.3,0.1

Type RM Length L Ch R = 1 ,673.5   ,181.5,182.7,183.4
XS GIS Cut Line= 2
     2076069.632      230892.292      2076422.97      231315.078
#Sta/Elev= 30
       0 1710.79    42.6 1698.37    55.8 1696.18    68.9  1694.8    95.1 1693.21
   111.5 1687.84   118.1 1685.97   121.4 1685.64   131.2 1687.45  149.571688.804
  152.741689.057   173.8  1690.9  196.011695.881   209.9 1698.79   229.6 1705.64
   255.8 1711.15   265.7 1714.44   282.1 1716.02   301.7 1720.51   324.7 1723.21
   344.4 1728.29   357.5 1730.82   370.6  1734.2   377.2  1735.2   423.1 1745.83
   485.4 1756.54   495.2 1757.52   505.1 1757.64     528 1761.13     551  1762.8
#Mann= 6 ,-1 , 0
       0     .12       0   111.5    .045       0   131.2     .06       0
  149.57     .12       0  152.74     .06       0  196.01     .12       0
Bank Sta=111.5,131.2
XS Rating Curve= 0 ,0
Exp/Cntr=0.3,0.1

Type RM Length L Ch R = 1 ,490.8   ,169.2,193.7,216.2
XS GIS Cut Line= 2
     2075973.646      231027.322     2076258.907      231391.901
#Sta/Elev= 30
       0 1700.52    22.8  1696.2    35.9 1690.89    42.4 1688.88    48.9 1687.49
    55.4 1686.71   79.761686.223   117.4 1687.06   127.1 1686.51   136.9 1685.19
   143.4 1683.71   146.7 1683.37     150 1683.53   156.5  1685.4     163 1686.41
     176 1691.21  180.79 1692.48  196.321695.958   211.9 1698.97   224.9 1700.86
   277.1 1706.08   303.2 1710.37  325.191711.999  341.471713.775   378.2 1718.38
   391.2 1721.08     414 1724.96   440.1 1728.59   453.1 1729.72   462.9 1731.02
#Mann= 8 ,-1 , 0
       0     .06       0   79.76     .12       0   136.9    .045       0
   156.5     .12       0  180.79     .06       0  196.32     .12       0
  325.19     .06       0  341.47     .12       0
#XS Ineff= 2 , 0
          121.06 1720.03
Permanent Ineff=
       F       F
Bank Sta=136.9,156.5
XS Rating Curve= 0 ,0
Exp/Cntr=0.3,0.1

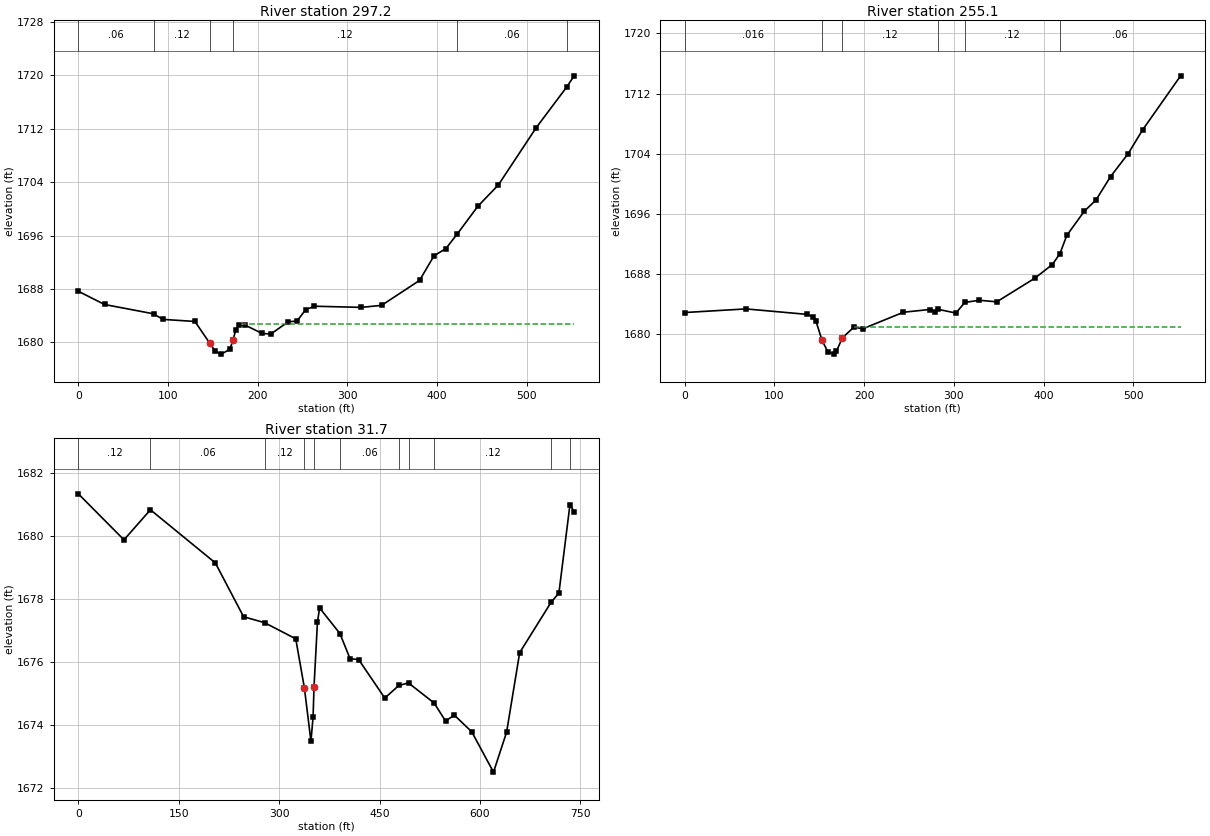
Type RM Length L Ch R = 1 ,297.2   ,44.5,42.1,50.8
XS GIS Cut Line= 3
     2075892.303      231100.532      2075929.48      231377.578
     2076200.313      231414.036
#Sta/Elev= 30
       0 1687.66    29.2 1685.68   83.921684.283    94.3 1683.45     130 1683.14
   146.3 1679.93   152.8 1678.65   159.3 1678.25     169 1678.97   172.3  1680.3
   175.5 1681.86   178.8 1682.56   185.3 1682.63   204.8 1681.36   214.5 1681.25
     234 1683.09   243.8  1683.2   253.5 1684.91   263.3 1685.42   315.3 1685.25
   338.1 1685.55   380.4 1689.28   396.6 1692.98   409.7 1694.04   422.51696.239
   445.4 1700.38   468.2 1703.56   510.5 1712.15  544.52 1718.24   552.8 1719.91
#Mann= 6 ,-1 , 0
       0     .06       0   83.92     .12       0   146.3    .045       0
   172.3     .12       0   422.5     .06       0  544.52     .12       0
#XS Ineff= 2 , 0
                          182.35         1682.82
Permanent Ineff=
       F       F
Bank Sta=146.3,172.3
XS Rating Curve= 0 ,0
Exp/Cntr=0.3,0.1

Type RM Length L Ch R = 1 ,255.1   ,219.4,223.3,215.4
XS GIS Cut Line= 3
     2075859.751      231126.573     2075896.928      231403.619
     2076167.761      231440.078
#Sta/Elev= 30
       0 1682.89    68.3 1683.37   136.5 1682.64     143 1682.33   146.3 1681.72
   152.8 1679.26   159.3  1677.7   165.8 1677.36     169 1677.72   175.5  1679.5
   188.5 1680.95   198.3 1680.72   243.8 1682.93     273 1683.29   279.5 1683.02
  282.351683.314   302.3 1682.82  312.171684.233   328.3 1684.52   347.8 1684.31
   390.1 1687.44   409.7 1689.26  418.141690.691   425.9 1693.14   445.4 1696.35
   458.5 1697.86   474.7 1700.96   494.2 1703.99   510.5 1707.18   552.8 1714.35
#Mann= 6 ,-1 , 0
       0    .016       0   152.8    .045       0   175.5     .12       0
  282.35    .016       0  312.17     .12       0  418.14     .06       0
#XS Ineff= 2 , 0
                          188.38         1680.97
Permanent Ineff=
       F       F
Bank Sta=152.8,175.5
XS Rating Curve= 0 ,0
Exp/Cntr=0.3,0.1

Type RM Length L Ch R = 1 ,31.7    ,48.9,31.7,16.8
XS GIS Cut Line= 4
     2075846.147      231126.276     2075727.657      231368.463
     2075745.713      231646.849     2075912.379      231742.335
#Sta/Elev= 30
       0 1681.34    68.2 1679.88  107.691680.834   204.6 1679.15   246.9 1677.44
  278.131677.252   324.8 1676.74   337.7 1675.18   347.5 1673.49   350.7 1674.27
  352.09 1675.22   357.2 1677.26   360.4 1677.72  390.751676.908   405.9 1676.11
   418.8 1676.08   457.8 1674.86  478.961675.262  493.231675.339  531.531674.703
   548.6 1674.13   561.6 1674.32   587.7 1673.79   620.2 1672.51   639.8 1673.78
   659.3  1676.3  706.431677.905   717.9 1678.19  734.421680.998   740.7 1680.77
#Mann= 11 ,-1 , 0
       0     .12       0  107.69     .06       0  278.13     .12       0
   337.7    .045       0  352.09     .12       0  390.75     .06       0
  478.96     .12       0  493.23     .06       0  531.53     .12       0
  706.43     .06       0  734.42     .12       0
Bank Sta=337.7,352.09
XS Rating Curve= 0 ,0
Exp/Cntr=0.3,0.1

Chan Stop Cuts=-1
Use User Specified Reach Order=0
Composite Channel Slope=5